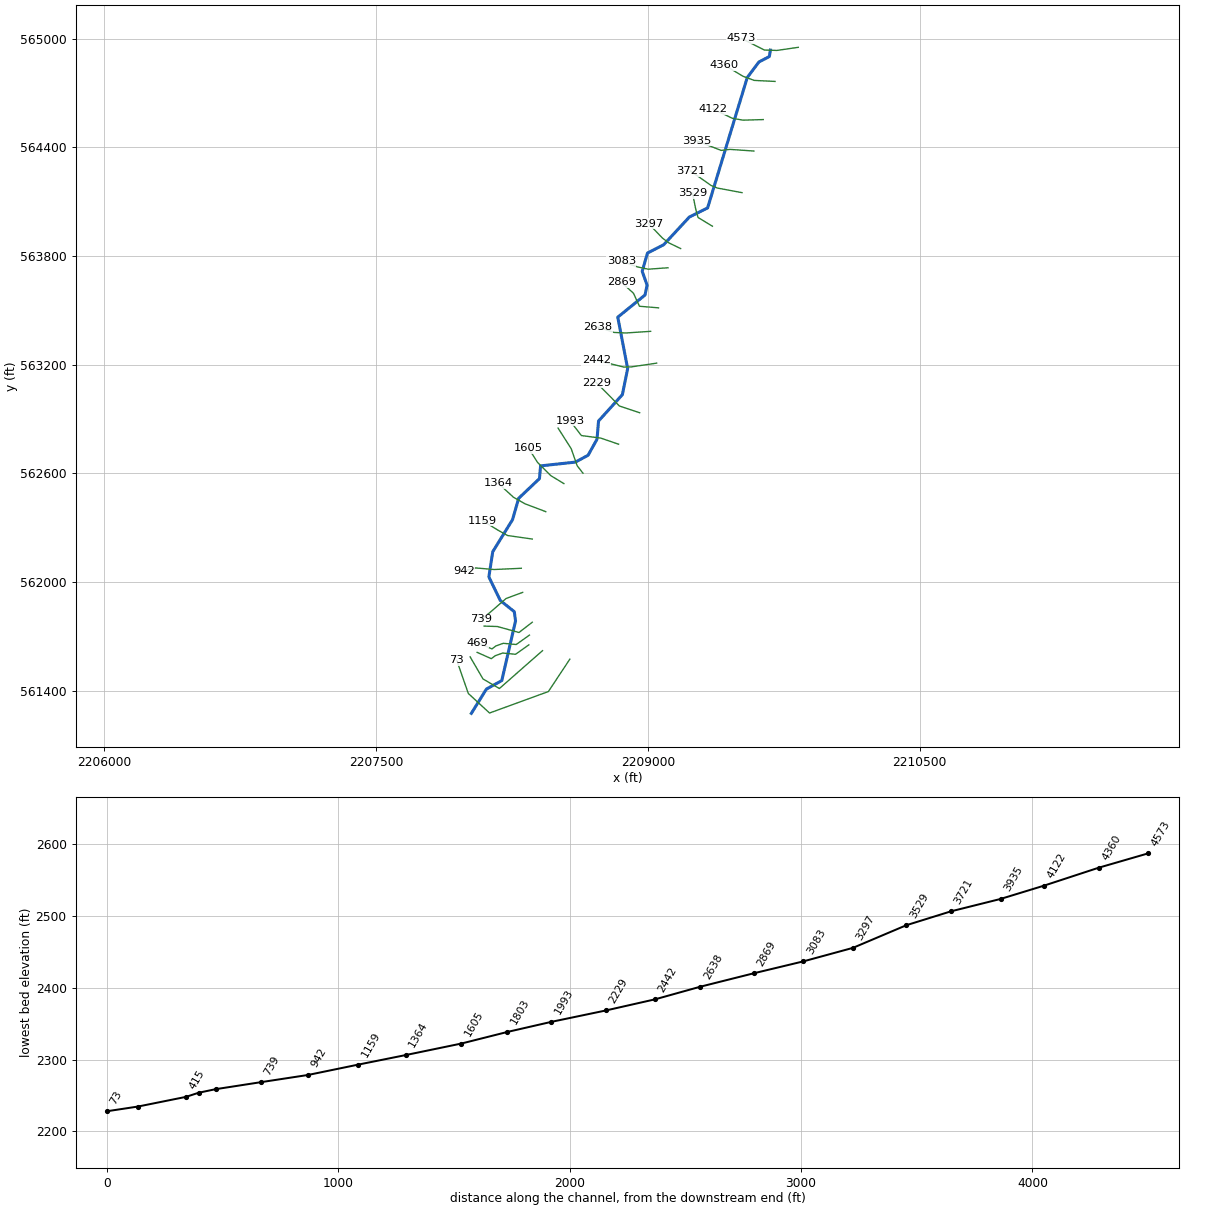
--- HICKLKRN.prj (project) ---

Proj Title=HICKLKRN
Current Plan=p01
Default Exp/Contr=0,0
English Units
Geom File=g01
Flow File=f01
Plan File=p01
Background Map Layer=Inundation Boundary (P100yr Value_0)
BEGIN DESCRIPTION:
----------MODEL BY WOOD PLC 2022----------
AFH study
Randolph County, WV
HEC-RAS Version: RAS 6.2
Vertical Datum: NAVD88
Projection: NAD 1983 StatePlane West Virginia S FIPS 4702 (US Feet)
Terrain: 1-meter LIDAR (FEMA Region III 3DEP collected 2016-2018)
Land Use: 2019 NLCD
Hydrologic Method:
WV SIR2010-5033 regression equations
Additional Model Notes:
None
END DESCRIPTION:
DSS Export Rating Curves= 0
DSS Export Rating Curve Sorted= 0
DSS Export Volume Flow Curves= 0
DXF OffsetX= 0
DXF OffsetY= 0
DXF ScaleX= 0
DXF ScaleY= 0

--- HICKLKRN.p01 (plan) ---

Plan Title=Floodplain
Program Version=6.20
Short Identifier=Floodplain
Geom File=g01
Flow File=f01
Subcritical Flow
K Sum by GR= 0
Std Step Tol= 0.01
Critical Tol= 0.01
Num of Std Step Trials= 20
Max Error Tol= 0.3
Flow Tol Ratio= 0.001
Split Flow NTrial= 30
Split Flow Tol= 0.02
Split Flow Ratio= 0.02
Log Output Level= 0
Friction Slope Method= 1
Unsteady Friction Slope Method= 2
Unsteady Bridges Friction Slope Method= 1
Parabolic Critical Depth
Global Vel Dist= 0 , 0 , 0
Global Log Level= 0
CheckData=True
Encroach Param=-1 ,0,0, 0
Mapping Interval=1HOUR
Computation Time Step Use Courant=        0
Computation Time Step Use Time Series=    0
Computation Time Step Count To Double=0
Computation Time Step Max Doubling=0
Computation Time Step Max Halving=0
Computation Time Step Residence Courant=0
Run HTab= 0
Run UNet= 0
Run Sediment= 0
Run PostProcess= 0
Run WQNet= 0
Run RASMapper=-1
UNET Theta= 0
UNET Theta Warmup= 0
UNET ZTol= 0
UNET ZSATol= 0
UNET MxIter= 0
UNET Max Iter WO Improvement= 0
UNET MaxInSteps= 0
UNET DtIC= 0
UNET DtMin= 0
UNET MaxCRTS= 0
UNET WFStab= 0
UNET SFStab= 0
UNET WFX= 1
UNET SFX= 1
UNET Gravity=32.174
UNET 1D Methodology=Finite Difference
UNET DSS MLevel= 1
UNET Pardiso=0
UNET DZMax Abort= 0
UNET Use Existing IB Tables= 0
UNET Froude Reduction=False
UNET Froude Limit= 0
UNET Froude Power= 0
UNET D1 Cores= 0
UNET WindReference=Eulerian
UNET WindDragFormulation=Hsu (1988)
UNET D2 Coriolis=0
UNET D2 Cores= 0
UNET D2 Theta= 1
UNET D2 Theta Warmup= 1
UNET D2 Z Tol= 0.01
UNET D2 Volume Tol= 0.01
UNET D2 Max Iterations= 20
UNET D2 Equation= 0
UNET D2 RampUpFraction=0.1
UNET D2 TimeSlices= 1
UNET D2 Turbulence Formulation=Non-Conservative (original)
UNET D2 Eddy Viscosity=0.3
UNET D2 Transverse Eddy Viscosity=0.1
UNET D2 Smagorinsky Mixing=0
UNET D2 BCVolumeCheck=0
UNET D2 Cores=0
UNET D2 SolverType=PARDISO (Direct)
UNET D2 Minimum Iterations= 2147483647
UNET D2 Maximum Iterations= 2147483647
UNET D2 Restart Number= 10
UNET D2 Relaxation Coeff=1.3
UNET D2 SOR Precondition Iterations= 10
UNET D2 ILUT Maximum Fill= 8
UNET D2 ILUT Tolerance=1E-08
UNET D1D2 MaxIter= 0
UNET D1D2 ZTol=0.01
UNET D1D2 QTol=0.1
UNET D1D2 MinQTol=1
Write IC File= 0
Write IC File at Fixed DateTime=0
Write IC File at Sim End=0
Echo Input=False
Echo Parameters=False
Echo Output=False
Write Detailed= 0
HDF Write Warmup=0
HDF Write Time Slices=0
HDF Flush=0
HDF Compression= 1
HDF Chunk Size= 1
HDF Spatial Parts= 1
HDF Use Max Rows=0
HDF Fixed Rows= 1
Calibration Method= 0
Calibration Iterations= 20
Calibration Max Change=0.05
Calibration Tolerance=0.2
Calibration Maximum=1.5
Calibration Minimum=0.5
Calibration Optimization Method= 1
WQ AD Non Conservative
WQ ULTIMATE=-1
WQ Max Comp Step=1HOUR
WQ Output Interval=15MIN
WQ Output Selected Increments= 0
WQ Output face flow=0
WQ Output face velocity=0
WQ Output face area=0
WQ Output face dispersion=0
WQ Output cell volume=0
WQ Output cell surface area=0
WQ Output cell continuity=0
WQ Output cumulative cell continuity=0
WQ Output face conc=0
WQ Output face dconc_dx=0
WQ Output face courant=0
WQ Output face peclet=0
WQ Output face adv mass=0
WQ Output face disp mass=0
WQ Output cell mass=0
WQ Output cell source sink temp=0
WQ Output nsm pathways=0
WQ Output nsm derived pathways=0
WQ Create Restart=0
WQ Fixed Restart=0
WQ System Summary=0
WQ Write To DSS=0
Sorting and Armoring Iterations= 10
XS Update Threshold= 0.02
Bed Roughness Predictor= 0
Hydraulics Update Threshold= 0.02
Energy Slope Method= 1
Volume Change Method= 1
Sediment Retention Method= 0
Sediment TS Multiplier= 1
Warm Up Method= 0
XS Weighting Method= 0
Number of US Weighted Cross Sections= 1
Number of DS Weighted Cross Sections= 1
Upstream XS Weight=0
Main XS Weight=1
Downstream XS Weight=0
Number of DS XS's Weighted with US Boundary= 1
Upstream Boundary Weight= 1
Weight of XSs Associated with US Boundary= 0
Number of US XS's Weighted with DS Boundary= 1
Downstream Boundary Weight= 0.5
Weight of XSs Associated with DS Boundary= 0.5
Percentile Method= 0
Sediment Output Level= 3
Mass or Volume Output= 0
Output Increment Type= 1
Profile and TS Output Increment= 1
Transport Output Increment 1
XS Output Flag= 0
XS Output Increment= 10
Read HDF5 Sediment Hotstart= 0
Sediment Hotstart Type= 0
Write Gradation File= 0
Read Gradation Hotstart= 0
Write HDF5 File= 1
Write Binary Output= 1
Write DSS Sediment File= 0
DSS Sediment Output Type= 1
SV Curve= 0
Specific Gage Flag= 0
Subcell Erosion Methods= 0
Subcell Deposition Methods= 0
Advection Scheme= 1
Matrix Solver= 0
Implicit Weighting Factor= 1
Maximum Outer Loop Convergence Iterations= 5
Convergence Maximum Absolute= 0.001
Convergence RMSE= 0.0001
Grain Fractions Max Abs Error= 0.001
Max Subgrid Regions= 1
Max Subgrid Length Scale= 3.402823E+38
Initial Layer Thickness= 3.402823E+38
Min Layer Thickness= 3.402823E+38
Max Layer Thickness= 3.402823E+38
Number of Layers= 5

--- HICKLKRN.f01 (steady flow) ---

Flow Title=Flow
Program Version=6.20
Number of Profiles= 1
Profile Names=P100yr
River Rch & RM=HICKLKRN,Main,4573
     353
River Rch & RM=HICKLKRN,Main,1159
     532
Boundary for River Rch & Prof#=HICKLKRN,Main            , 1
Up Type= 0
Dn Type= 3
Dn Slope=0.04855
DSS Import GetInterval= 0
DSS Import GetPeak= 0
DSS Import FillOption= 0

--- HICKLKRN.g01 (geometry) ---

Geom Title=Geometry
Program Version=6.20

River Reach=HICKLKRN        ,Main
Reach XY= 30
2209676.27638111564936.8793893472209670.45802619564901.336868141
2209612.67739759564871.2309835222209548.53365796564785.674688337
2209329.57375536 564065.64360614     2209228.842      564015.421
2209086.92741631563862.3294871132208997.82426486563816.648966208
     2208968.558      563715.758     2208995.524       563639.33
     2208984.065      563584.816     2208833.718      563462.594
     2208888.232      563178.566     2208859.065      563034.816
     2208727.468       562889.33     2208719.221      562789.035
2208669.99436564562700.543142499     2208600.037      562662.594
     2208407.676      562641.761     2208401.354      562571.405
     2208286.843      562462.941     2208252.815      562344.886
     2208143.573      562168.061     2208122.154      562028.889
 2208185.1733086561898.632945388     2208262.444      561836.717
2208269.40273281561786.028470201     2208193.338      561456.459
2208108.49424432561409.553672449     2208025.402      561275.543

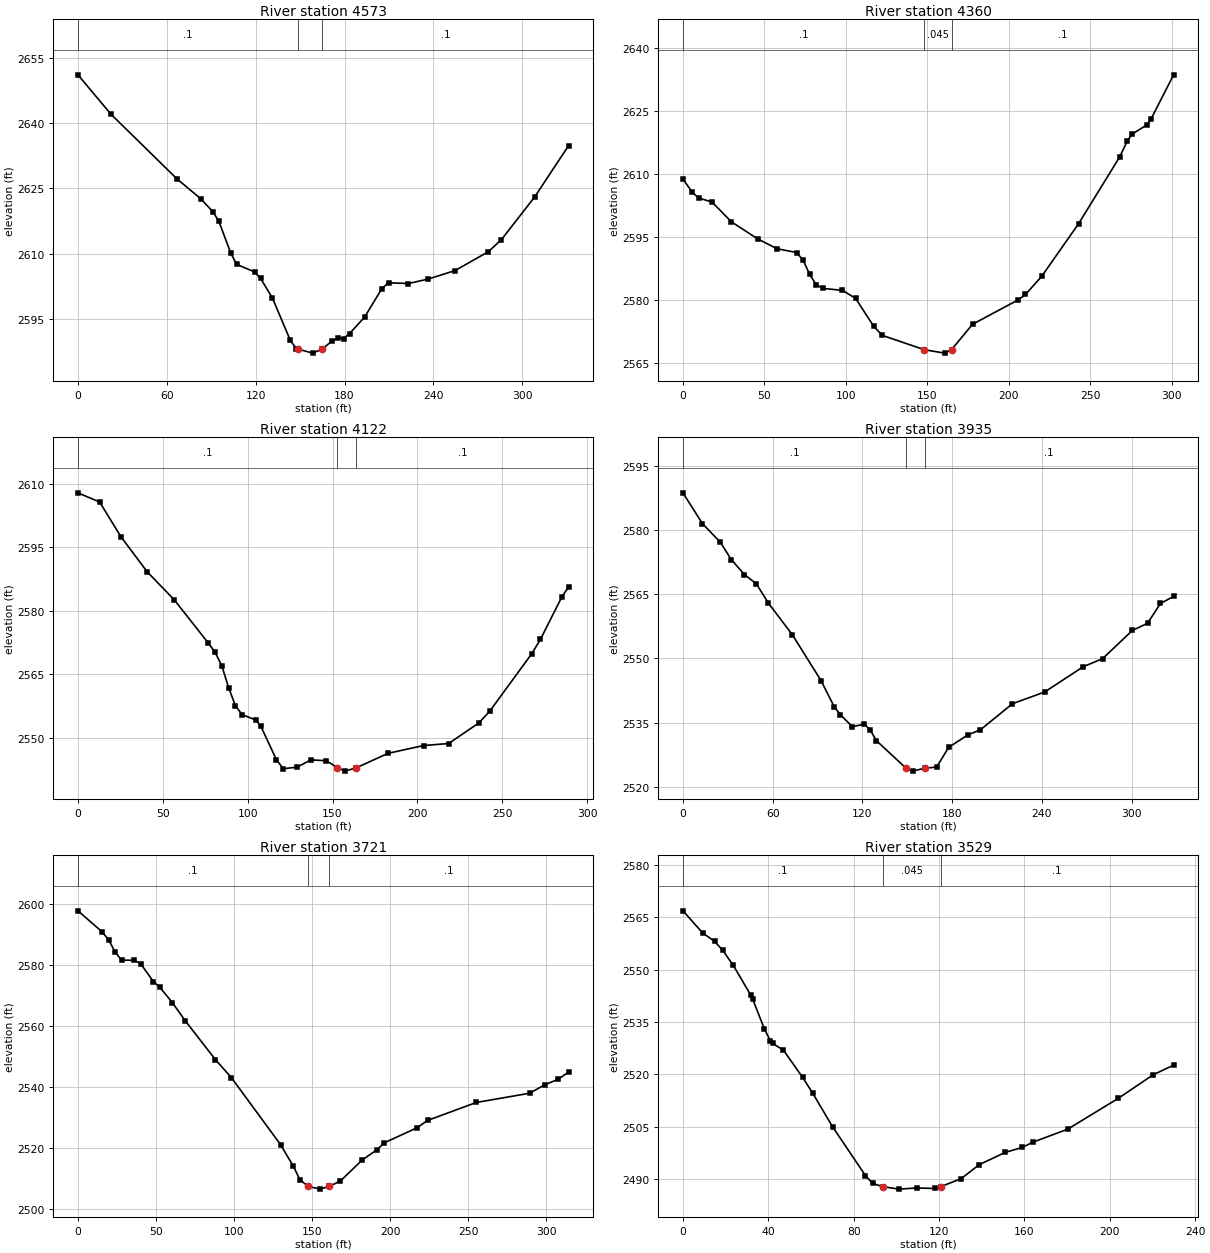
Type RM Length L Ch R = 1 ,4573    ,212.5,212.3,207.4
XS GIS Cut Line= 4
2209830.26715265564952.264799878 2209711.8949706  564935.0185217
2209643.17747951564937.1364457452209515.67345668565001.827663463
#Sta/Elev= 30
       0 2651.08    22.2 2642.06    66.8 2627.19      83 2622.59      91 2619.66
    95.1 2617.47   103.2  2610.1   107.2 2607.52   119.3 2605.79   123.3 2604.31
   131.3 2599.81   143.4 2590.05   147.4  2588.2  148.812588.051   158.4 2587.14
  164.812588.052   171.4 2589.88   175.4 2590.57   179.4  2590.5   183.4 2591.64
   193.6 2595.44   205.2 2601.96   209.7 2603.31   223.1 2603.13   236.6 2604.17
   254.5 2606.09   277.1 2610.44   285.9 2613.21   308.4 2623.04   331.3 2634.83
#Mann= 3 ,-1,0
       0      .1       0  148.81    .045       0  164.81      .1       0
Bank Sta=148.81,164.81
XS Rating Curve= 0 ,0
Exp/Cntr(USF)=0,0
Exp/Cntr=0.3,0.1

Type RM Length L Ch R = 1 ,4360    ,237.1,238.7,239.5
XS GIS Cut Line= 4
2209701.92301962564763.9326957232209586.65231933564769.610558617
2209525.66419002564792.1070306172209422.25391702564854.269697572
#Sta/Elev= 30
       0 2608.85     5.8 2605.65     9.8  2604.3    17.8 2603.38    29.8 2598.63
    45.8 2594.59    57.8 2592.22    69.8 2591.32    73.8 2589.44    77.8  2586.1
    81.8 2583.61    85.9 2582.77    97.9 2582.28   105.9 2580.41     117 2573.77
   122.3 2571.56  148.072568.143   160.6 2567.32  164.842568.143   177.7  2574.2
   205.8 2580.04   210.2 2581.31   220.2 2585.66   242.8  2598.2   267.9 2614.05
   272.6 2617.84   275.5 2619.53   284.8 2621.79   287.2 2623.12   301.1 2633.71
#Mann= 3 ,-1,0
       0      .1       0  148.07    .045       0  164.84      .1       0
Bank Sta=148.07,164.84
XS Rating Curve= 0 ,0
Exp/Cntr=0.3,0.1

Type RM Length L Ch R = 1 ,4122    ,183.9,186.3,187.9
XS GIS Cut Line= 4
2209636.92199065564553.3984257482209525.32727914564550.142888368
2209465.69964057564560.5413962242209360.61201373564611.773020477
#Sta/Elev= 30
       0 2607.82    12.8 2605.64    25.3 2597.47    40.8 2589.17    56.8 2582.53
    76.8 2572.34    80.8 2570.18    84.8 2566.92    88.8 2561.78    92.8 2557.51
    96.8 2555.43   104.8 2554.18   107.7 2552.74   116.9 2544.84   120.9 2542.67
   129.1 2543.03   137.2 2544.75   146.4 2544.56  152.832542.911   157.5  2542.1
  164.112542.919   182.8 2546.31   203.7 2548.15   218.4 2548.62   236.2 2553.48
   242.6 2556.24   267.3 2569.79   272.5 2573.22   285.1 2583.25   289.1  2585.6
#Mann= 3 ,-1,0
       0      .1       0  152.83    .045       0  164.11      .1       0
Bank Sta=152.83,164.11
XS Rating Curve= 0 ,0
Exp/Cntr=0.3,0.1

Type RM Length L Ch R = 1 ,3935    ,217.9,214.7,211.7
XS GIS Cut Line= 4
2209585.16930462564379.6938980382209453.00153822564388.828945925
2209404.44766501564383.1466993012209268.02072454 564436.83900934
#Sta/Elev= 30
       0 2588.65      13 2581.49    25.1 2577.07    32.3 2573.09    41.1 2569.59
    49.1 2567.42    57.1 2562.93    73.2 2555.52    92.3 2544.86   101.2  2538.7
   105.2 2536.93   113.3 2534.07   121.3 2534.71   125.3 2533.26   129.3 2530.84
  149.112524.413   153.5 2523.72   161.5 2524.39   169.6 2524.67   177.6 2529.25
   190.3 2532.14   198.9 2533.38   220.3 2539.45   241.8 2542.18   267.6 2548.08
   280.5 2549.95   300.4 2556.53   310.6 2558.22   319.2 2562.83     328 2564.48
#Mann= 3 ,-1,0
       0      .1       0  149.11    .045       0   161.5      .1       0
Bank Sta=149.11,161.5
XS Rating Curve= 0 ,0
Exp/Cntr=0.3,0.1

Type RM Length L Ch R = 1 ,3721    ,205.3,192.3,183
XS GIS Cut Line= 4
2209519.64990738564149.9618420392209384.03739635564175.273092759
2209349.09257517564189.4942247282209235.75935821564269.063022741
#Sta/Elev= 30
       0 2597.87    15.7 2590.87    19.8 2588.19    23.9 2584.26    27.9 2581.69
    36.1 2581.61    40.2 2580.48    48.3 2574.62    52.4 2572.78    60.5 2567.69
    68.6 2561.82      88 2549.01    98.3 2543.04   129.7 2521.08     138 2513.91
   142.1 2509.56  147.322507.366   155.1 2506.44  160.862507.368     168 2509.08
   182.1 2516.05   191.5 2519.38   196.2 2521.66   216.9 2526.54   223.9 2529.01
     255  2534.9   289.2 2537.94     299 2540.75   307.4  2542.5   314.2  2544.9
#Mann= 3 ,-1,0
       0      .1       0  147.32    .045       0  160.86      .1       0
Bank Sta=147.32,160.86
XS Rating Curve= 0 ,0
Exp/Cntr=0.3,0.1

Type RM Length L Ch R = 1 ,3529    ,224,231.5,237.8
XS GIS Cut Line= 4
2209356.06141276563964.6982601122209276.84672335564012.958009634
2209264.51130673564056.8396515262209246.31251019 564146.59846708
#Sta/Elev= 30
       0 2566.79     9.2  2560.5    14.8 2558.06    18.6 2555.53    23.6 2551.18
    31.7 2542.76    32.7 2541.54    38.1 2533.09      41 2529.58      42 2528.89
    47.1 2526.92    56.1 2519.13    60.8 2514.62    70.1 2505.03    85.5 2491.06
    88.9 2488.79   93.822487.854   101.3 2487.17   109.6 2487.51   117.9 2487.36
  120.742487.854   130.4 2490.18   138.7 2494.12   150.9 2497.66   159.1 2499.12
   163.9 2500.58   180.3 2504.33     204 2513.15   220.3 2519.88   229.9 2522.64
#Mann= 3 ,-1,0
       0      .1       0   93.82    .045       0  120.74      .1       0
Bank Sta=93.82,120.74
XS Rating Curve= 0 ,0
Exp/Cntr=0.3,0.1

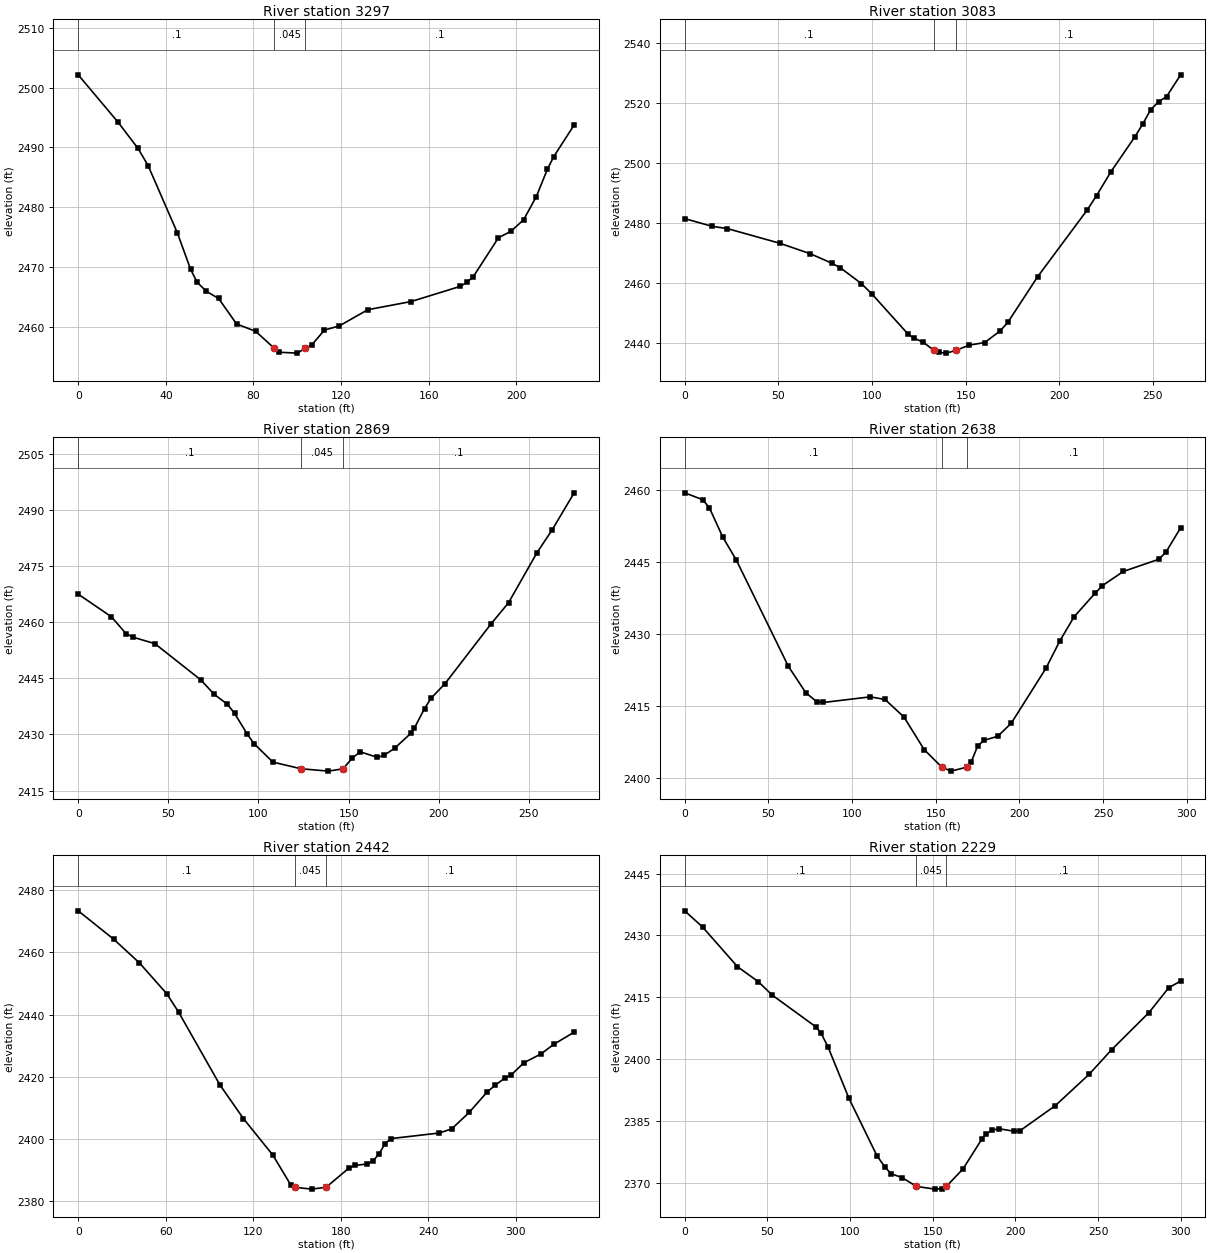
Type RM Length L Ch R = 1 ,3297    ,209.7,214.4,214.6
XS GIS Cut Line= 4
2209180.87182482563841.3240315072209113.77832499563873.720545083
2209080.27092067563899.3405918962209004.14138247563978.390784734
#Sta/Elev= 30
       0 2502.16    18.1 2494.27    27.3 2489.84    31.9 2486.97    45.2 2475.75
    51.3  2469.6    54.3 2467.42    58.5 2465.91    64.1 2464.71    72.3 2460.44
      81 2459.22   89.512456.367    91.6 2455.71     100 2455.56  103.622456.366
   106.7 2456.96   112.4 2459.42   119.2 2460.12   132.2 2462.83     152  2464.2
   174.5 2466.75   177.5 2467.44   180.3 2468.33   191.8 2474.86   197.6 2475.98
   203.3 2477.88   209.1 2481.74   214.2 2486.37   217.1 2488.47   226.4 2493.77
#Mann= 3 ,-1,0
       0      .1       0   89.51    .045       0  103.62      .1       0
Bank Sta=89.51,103.62
XS Rating Curve= 0 ,0
Exp/Cntr=0.3,0.1

Type RM Length L Ch R = 1 ,3083    ,222.6,213.7,199.3
XS GIS Cut Line= 4
2209110.95692248563735.3957442012209002.22671993563727.428176665
2208942.66269544563740.0614441642208853.04239741563771.310670263
#Sta/Elev= 30
       0 2481.46    14.8 2478.87    22.8 2478.14    50.9 2473.25      67  2469.8
    78.5 2466.66    83.1 2465.12    94.4 2459.84   100.2 2456.24   119.3 2443.04
   122.3 2441.77   127.5 2440.33  132.942437.697   135.7 2436.99   139.7 2436.74
  145.012437.697     152  2439.4   160.2 2440.26   168.4  2444.1   172.5 2446.93
   188.4 2462.09   214.9 2484.31   219.9 2489.09   227.6 2497.05   240.3 2508.59
   244.6 2512.92   248.8 2517.65     253  2520.3   257.3 2522.03   264.8 2529.26
#Mann= 3 ,-1,0
       0      .1       0  132.94    .045       0  145.01      .1       0
Bank Sta=132.94,145.01
XS Rating Curve= 0 ,0
Exp/Cntr=0.3,0.1

Type RM Length L Ch R = 1 ,2869    ,218.9,230.9,240.8
XS GIS Cut Line= 4
2209058.53698867563514.1412972842208953.38121832563522.907003508
2208920.40101567563594.7799234322208853.14050332563655.259327776
#Sta/Elev= 30
       0 2467.49    18.4 2461.45    26.5 2456.95    30.5 2455.98    42.5 2454.27
      68 2444.58    75.4 2440.74    82.8 2438.05    86.7 2435.65    93.9    2430
    97.6 2427.51     108 2422.61  123.61 2420.83   138.8  2420.2  146.95 2420.83
     152 2423.68   156.4 2425.36     166 2423.88   169.6 2424.39   175.6 2426.35
   184.6 2430.34   186.5 2431.73   192.1 2436.92   195.7 2439.66   203.5  2443.6
   228.9 2459.49   238.7  2465.2   254.4 2478.51   262.9 2484.67   275.1 2494.57
#Mann= 3 ,-1,0
       0      .1       0  123.61    .045       0  146.95      .1       0
Bank Sta=123.61,146.95
XS Rating Curve= 0 ,0
Exp/Cntr=0.3,0.1

Type RM Length L Ch R = 1 ,2638    ,195.5,195.8,195.1
XS GIS Cut Line= 4
2209014.92494139563384.4640681342208878.10259699563375.354357103
2208813.33933772563378.3518482272208723.77730201563407.954118089
#Sta/Elev= 30
       0 2459.33    10.8  2457.9    14.8 2456.19    22.8 2450.11    30.8  2445.4
      62 2423.26    72.4 2417.79    78.9 2415.94    82.9 2415.78   110.9 2416.95
   119.7  2416.4     131 2412.77   143.1 2405.99  153.652402.332   159.1 2401.52
  168.452402.333   171.1 2403.34   175.1  2406.8   179.1 2407.94   187.1 2408.77
   195.1 2411.47   215.8 2422.86   224.2 2428.61   232.7  2433.6   245.3 2438.51
   249.5 2440.04   262.1    2443   283.2 2445.52   287.4 2446.94   296.3 2452.06
#Mann= 3 ,-1,0
       0      .1       0  153.65    .045       0  168.45      .1       0
Bank Sta=153.65,168.45
XS Rating Curve= 0 ,0
Exp/Cntr=0.3,0.1

Type RM Length L Ch R = 1 ,2442    ,220.8,212.8,204.9
XS GIS Cut Line= 4
2209048.21759966563208.8301926292208907.09136499563187.957640282
2208866.27146747 563187.35908488 2208714.3051624 563225.02782658
#Sta/Elev= 30
       0 2473.29    24.3 2464.19      42 2456.56    60.7 2446.68    68.8  2440.8
    97.1 2417.45   113.3 2406.57   133.5 2394.85   145.6 2385.39  148.462384.532
   160.1 2383.93     1702384.531   185.6 2390.67   189.8 2391.54     198    2392
   202.1 2392.97   206.3 2395.21   210.4 2398.53   214.5 2400.16   247.5 2401.94
   256.1 2403.26   268.1 2408.55   280.4  2415.1   285.8 2417.23   292.8 2419.69
   296.9  2420.6   305.6 2424.49   317.5 2427.38   326.3 2430.48   340.1 2434.32
#Mann= 3 ,-1,0
       0      .1       0  148.46    .045       0     170      .1       0
Bank Sta=148.46,170
XS Rating Curve= 0 ,0
Exp/Cntr=0.3,0.1

Type RM Length L Ch R = 1 ,2229    ,230.2,236.2,240.6
XS GIS Cut Line= 4
2208954.38843358562935.1028308292208842.09271395562972.532072487
2208799.66208973563016.7102794562208714.69544708563101.876818766
#Sta/Elev= 30
       0 2435.95    10.8 2432.03    31.9 2422.41    44.5 2418.75    52.9 2415.51
    79.3  2407.8    82.4 2406.31    86.7 2402.89    99.3 2390.46   116.2 2376.56
   121.1 2373.75   124.8 2372.15   131.5 2371.19  140.092369.063   151.3  2368.4
   155.8 2368.53  158.232369.064   168.3  2373.3   179.6 2380.47   182.4 2381.77
   185.9 2382.72   190.2 2383.05   199.4 2382.44   202.9 2382.61   224.2 2388.69
   244.6 2396.28   258.2 2402.25   280.8 2411.27   292.7 2417.28   299.9  2418.9
#Mann= 3 ,-1,0
       0      .1       0  140.09    .045       0  158.23      .1       0
Bank Sta=140.09,158.23
XS Rating Curve= 0 ,0
Exp/Cntr=0.3,0.1

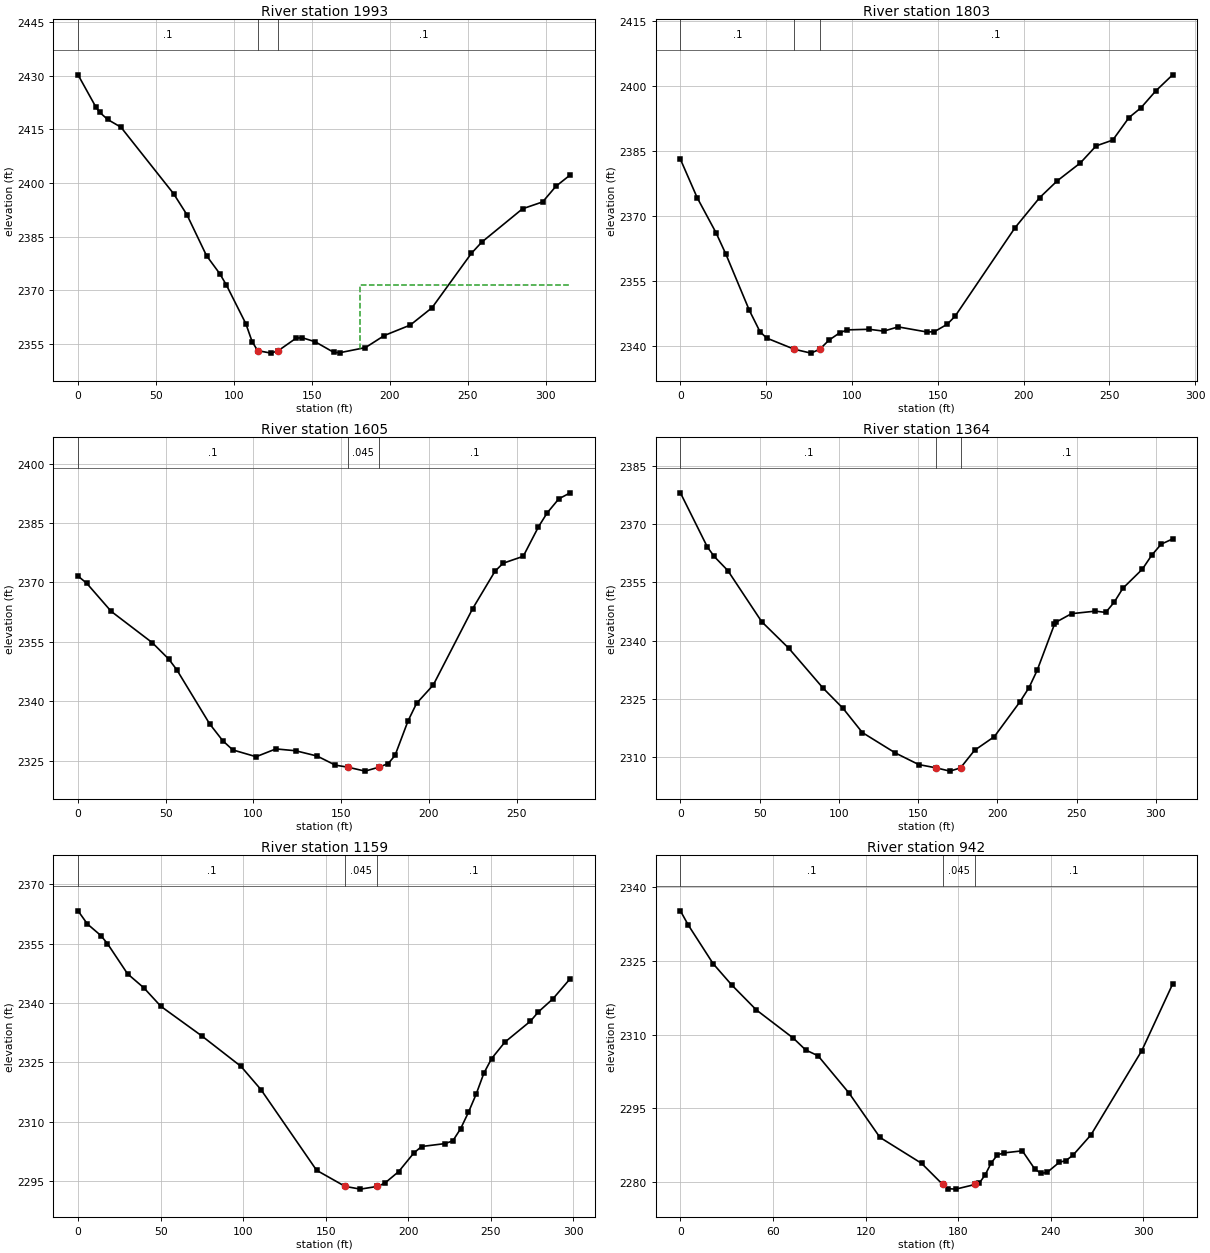
Type RM Length L Ch R = 1 ,1993    ,197.7,189.7,182.8
XS GIS Cut Line= 4
2208838.14474287562761.4002480332208740.39277942562794.966197655
2208632.88319526562809.1256886372208569.48918209562891.271249737
#Sta/Elev= 30
       0 2430.22    11.6  2421.1      14 2419.71      19 2417.75    27.5  2415.6
    61.3 2397.01    69.8 2391.17    82.4 2379.71    90.9 2374.67    95.1 2371.54
   107.6 2360.72   111.6 2355.74  115.152353.199   123.7  2352.5  128.252353.135
   139.9  2356.7   143.9 2356.78     152 2355.68   164.1 2352.68   168.1 2352.64
   184.3 2354.05   196.4 2357.42     213 2360.33     227 2365.19   252.2 2380.36
   258.8 2383.47     285 2392.81   297.9 2394.73   306.4 2399.09   315.6 2402.26
#Mann= 3 ,-1,0
       0      .1       0  115.15    .045       0  128.25      .1       0
#XS Ineff= 2 , 0
                          181.06         2371.66
Permanent Ineff=
       F       F
Bank Sta=115.15,128.25
XS Rating Curve= 0 ,0
Exp/Cntr=0.3,0.1

Type RM Length L Ch R = 1 ,1803    ,193.5,198.4,202.5
XS GIS Cut Line= 4
2208641.53975071562601.4076438852208609.29888399562643.001486718
2208576.77672391562736.3728500492208504.05533105 562850.55038343
#Sta/Elev= 30
       0 2383.17     9.8 2374.28    20.8 2366.19    26.5 2361.29    40.2 2348.31
    46.4 2343.39    50.3 2341.93   66.332339.361    76.1 2338.46   81.252339.364
    86.6 2341.45    92.9 2343.16    97.3 2343.82     110 2343.96   118.5 2343.53
   126.9 2344.51   143.9 2343.32   148.1 2343.42   155.4 2345.09   160.1 2346.96
   195.1 2367.41   209.4 2374.31   219.6 2378.17   233.1 2382.31   242.3 2386.24
     252 2387.58   261.5 2392.79   268.4 2395.01   277.1 2398.93   286.9 2402.63
#Mann= 3 ,-1,0
       0      .1       0   66.33    .045       0   81.25      .1       0
Bank Sta=66.33,81.25
XS Rating Curve= 0 ,0
Exp/Cntr=0.3,0.1

Type RM Length L Ch R = 1 ,1605    ,238,240.7,242.2
XS GIS Cut Line= 4
2208536.35901251562543.9875096032208464.57356691562587.475024769
2208390.39631004562661.6880016022208341.18341239562739.072409418
#Sta/Elev= 30
       0 2371.59     4.9 2369.81    18.9 2362.69    42.3 2354.79    51.7 2350.65
    56.3 2347.94      75  2334.3    82.5 2330.03    88.2 2327.71   101.5 2325.99
   112.8 2327.96   124.1 2327.49   136.3 2326.16   146.7 2323.86  153.642323.362
   163.7 2322.35  171.592323.363   176.8 2324.25   180.7  2326.3   188.1    2335
     193 2339.47   202.5 2344.09   224.9 2363.33   237.7 2372.82   242.3 2374.84
   253.8 2376.59   262.5 2384.05   267.5 2387.59   274.1 2391.11   280.6 2392.62
#Mann= 3 ,-1,0
       0      .1       0  153.64    .045       0  171.59      .1       0
Bank Sta=153.64,171.59
XS Rating Curve= 0 ,0
Exp/Cntr=0.3,0.1

Type RM Length L Ch R = 1 ,1364    ,205.2,205.2,204.8
XS GIS Cut Line= 4
2208436.10332796562389.0687475072208321.66467057562432.459677804
2208258.38035298562468.3017744022208173.01001646562546.003643256
#Sta/Elev= 30
       0 2378.11      17 2364.14    21.3  2361.7    29.9 2358.06    51.3 2344.86
    68.4    2338      90 2327.73   102.6 2322.51   114.8 2316.26   135.7 2310.97
   150.4 2307.99  161.472307.135   170.1  2306.3  176.752307.135   185.6 2311.67
   198.1  2315.2   214.3 2324.21     220 2327.86   225.1 2332.29     236 2344.16
   236.9 2344.71   246.8 2346.93   261.8 2347.58   268.4 2347.25   273.8 2349.93
   279.2 2353.48   291.5 2358.41   297.4 2362.01   303.4 2364.87   310.6 2366.21
#Mann= 3 ,-1,0
       0      .1       0  161.47    .045       0  176.75      .1       0
Bank Sta=161.47,176.75
XS Rating Curve= 0 ,0
Exp/Cntr=0.3,0.1

Type RM Length L Ch R = 1 ,1159    ,212.5,217.6,221.4
XS GIS Cut Line= 4
2208361.84387741562237.8791513682208225.29970947562257.300525516
2208170.35422166562288.0266672142208087.67676267562339.211630748
#Sta/Elev= 30
       0 2363.27     5.7 2359.93    13.8 2357.04    17.8    2355      30 2347.36
    39.8 2343.85    50.2 2339.15    75.1 2331.64    98.7 2323.99   110.8 2318.12
   144.5 2297.75  161.752293.691     171    2293  181.322293.689   185.7 2294.48
   194.2 2297.43   203.4 2302.14   208.1 2303.76   222.3  2304.5     227  2305.2
   231.7 2308.25   236.4 2312.36   241.1 2316.96   245.8 2322.29   250.5 2325.98
   258.5 2330.11     274 2335.41   278.8 2337.75   287.6 2341.05   298.1 2346.15
#Mann= 3 ,-1,0
       0      .1       0  161.75    .045       0  181.32      .1       0
Bank Sta=161.75,181.32
XS Rating Curve= 0 ,0
Exp/Cntr=0.3,0.1

Type RM Length L Ch R = 1 ,942     ,192.6,202.3,209.2
XS GIS Cut Line= 4
2208301.31945937562076.5228466072208151.65979502562069.685355975
2208049.60386536562078.3224288622207984.80640422562062.400744705
#Sta/Elev= 30
       0 2335.22     5.1 2332.32    21.2 2324.46    33.2 2320.14    49.2 2315.04
    73.2 2309.28    81.2 2306.88    89.2  2305.7   109.3  2298.1   129.3 2289.08
   156.3 2283.79  169.952279.504   173.4 2278.63   178.5 2278.54  191.162279.504
   193.5 2279.69   197.5 2281.43   201.5 2283.92   205.5 2285.51   209.5 2285.91
   221.6 2286.34   229.6 2282.66   233.6 2281.76   237.6 2281.93   245.6 2284.02
   249.7 2284.33   254.4 2285.44   266.1  2289.6     299 2306.73     319  2320.3
#Mann= 3 ,-1,0
       0      .1       0  169.95    .045       0  191.16      .1       0
Bank Sta=169.95,191.16
XS Rating Curve= 0 ,0
Exp/Cntr=0.3,0.1

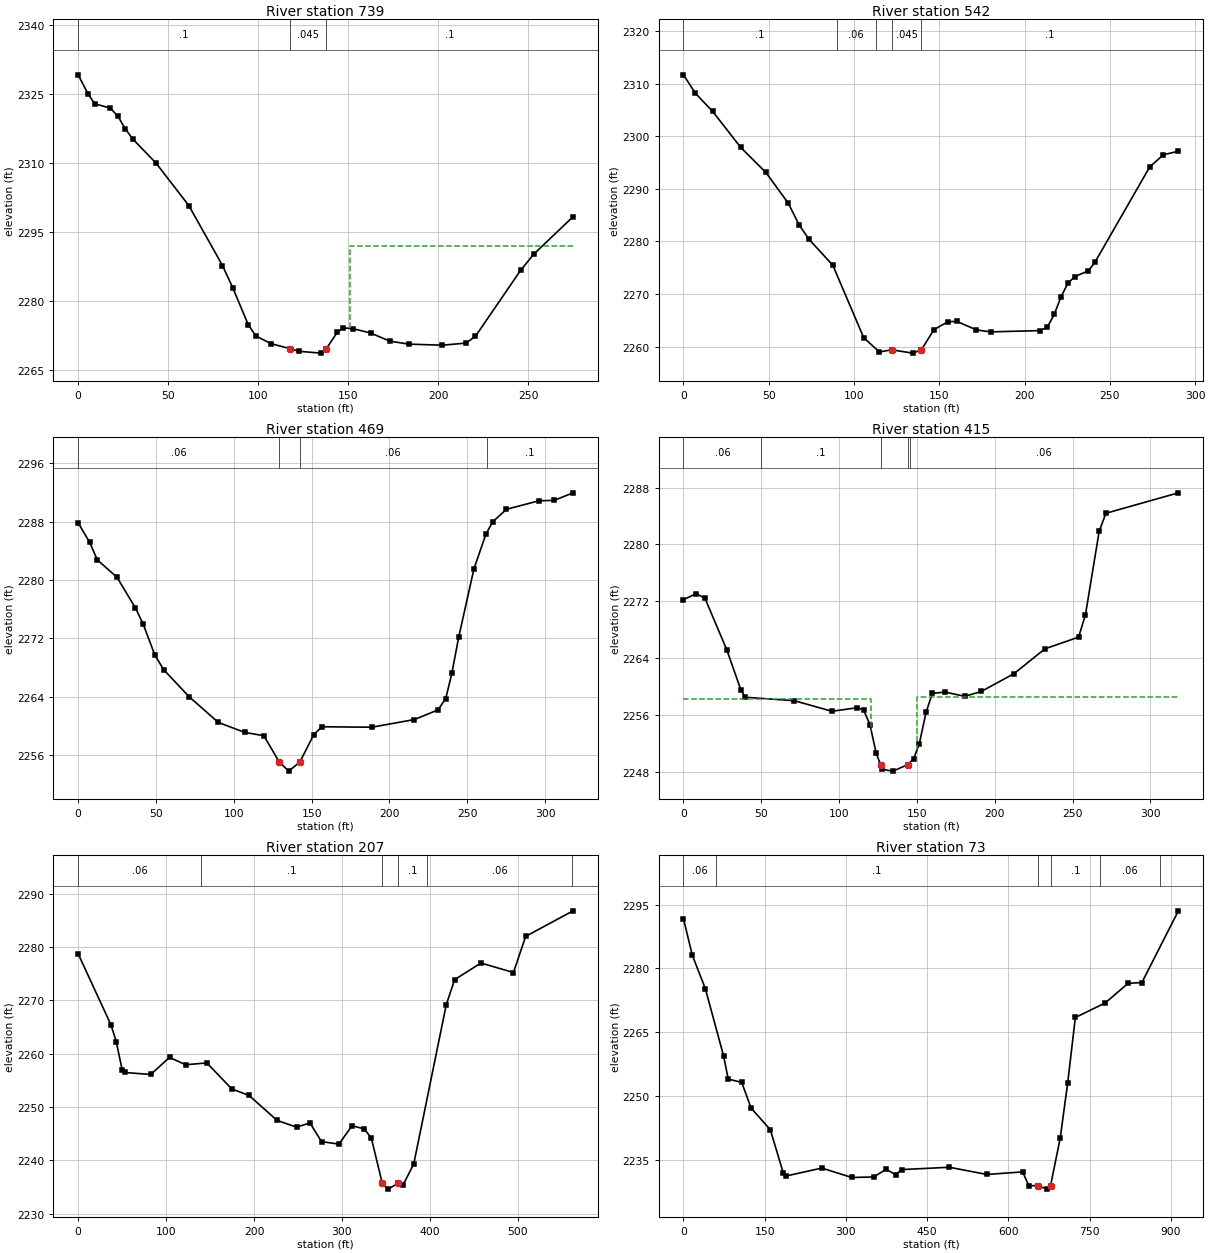
Type RM Length L Ch R = 1 ,739     ,206,197.1,188.1
XS GIS Cut Line= 4
2208308.84961881561943.4420532152208217.65030139561909.900110185
 2208121.0953846561826.4961548252208081.16566237561796.034939853
#Sta/Elev= 30
       0  2329.1     5.4 2325.03     9.2  2322.8    17.8 2321.87      22 2320.15
    26.3 2317.29    30.3 2315.17    43.3 2309.89    61.5 2300.66    80.2 2287.63
      86 2282.71    94.5 2274.78    98.7 2272.31   107.2 2270.64  117.732269.545
   122.8 2268.97     135 2268.58  137.922269.545   144.1 2273.17   147.2 2274.06
   152.6 2273.92   162.5 2272.95   173.1  2271.2   183.7 2270.54   202.3  2270.3
   215.4 2270.76   220.7 2272.21     246 2286.67   253.3 2290.15     275 2298.24
#Mann= 3 ,-1,0
       0      .1       0  117.73    .045       0  137.92      .1       0
#XS Ineff= 2 , 0
                          150.97         2291.86
Permanent Ineff=
       F       F
Bank Sta=117.73,137.92
XS Rating Curve= 0 ,0
Exp/Cntr=0.3,0.1

Type RM Length L Ch R = 1 ,542     ,72.5,73.2,75.1
BEGIN DESCRIPTION:
structure xs 4
END DESCRIPTION:
XS GIS Cut Line= 4
2208361.74534543561778.7060571182208288.40901055561722.048689187
2208169.62537333561754.9006494622208095.37193192561757.343656518
#Sta/Elev= 30
       0 2311.65       7 2308.14    17.1  2304.7    33.6 2297.84    48.3  2293.1
    61.4 2287.27    67.8 2283.14    73.5 2280.43    87.6 2275.43   105.7 2261.68
   114.9 2258.97     122 2259.38   134.4 2258.75  139.522259.378   146.9 2263.23
   155.2 2264.73   160.4 2264.77   171.8 2263.16   180.1 2262.79   209.1 2263.03
   213.3 2263.67   217.4  2266.1   221.4 2269.48   225.4 2272.01   229.4 2273.29
   237.4 2274.39   241.4 2276.09   273.4 2294.14   281.4 2296.46   290.2 2297.12
#Mann= 5 ,-1,0
       0      .1       0      90     .06       0  112.67      .1       0
     122    .045       0  139.52      .1       0
Bank Sta=122,139.52
XS Rating Curve= 0 ,0
Exp/Cntr(USF)=0,0
Exp/Cntr=0.3,0.1

Type RM Length L Ch R = 1 ,469     ,54.2,54.3,54.1
BEGIN DESCRIPTION:
structure xs 3
END DESCRIPTION:
XS GIS Cut Line= 6
2208346.21880987 561707.666057052208272.84516928561655.593441244
2208201.64483631561662.332066873 2208160.6617406561647.646457577
2208139.19803309561631.2759914562208061.02471951 561666.11936355
#Sta/Elev= 30
       0 2287.86     7.4 2285.17    12.3 2282.78      25 2280.37    36.8 2276.18
    41.7    2274    49.2 2269.75    54.9 2267.72    71.2 2264.02      90 2260.48
     107  2259.1   119.3 2258.65  129.232255.036   135.3 2253.79  142.452255.038
   151.3 2258.76   156.6 2259.88   188.6 2259.81   216.1 2260.87   231.2 2262.19
   236.2 2263.75   240.1  2267.2   244.5 2272.15   254.3 2281.53     262  2286.3
   266.4    2288   275.2 2289.71   296.1 2290.88   305.8 2290.93     318 2291.97
#Mann= 4 ,-1,0
       0     .06       0  129.23    .045       0  142.45     .06       0
  262.44      .1       0
#XS Ineff= 2 , 0
          111.23  2258.2  160.45          2258.5
Permanent Ineff=
       F       F
Bank Sta=129.23,142.45
XS Rating Curve= 0 ,0
Exp/Cntr(USF)=0,0
Exp/Cntr=0.3,0.1

Type RM Length L Ch R = 1 ,415     ,210.6,207.5,203
BEGIN DESCRIPTION:
structure xs 2
END DESCRIPTION:
XS GIS Cut Line= 6
2208342.82114125561653.8042389562208269.44750066 561601.73162315
2208198.24716768561608.4702487792208157.26407198561593.784639483
2208135.80036447561577.4141733622208057.62705089561612.257545456
#Sta/Elev= 30
       0 2272.21     8.1 2273.06    13.8 2272.41    27.8 2265.17    36.8 2259.55
    39.6 2258.47    71.2 2257.99    95.4  2256.5   111.7    2257   115.7  2256.7
   119.8 2254.62   123.8 2250.62  126.662248.969   127.8 2248.31   134.6 2248.07
  143.992248.969   147.9 2249.81   151.5  2251.9   155.9 2256.37   159.9 2259.02
   168.2  2259.2   180.7  2258.6   191.4 2259.29   212.4  2261.8   232.3  2265.3
   253.9 2266.94   258.3  2270.1   267.1 2281.83   271.4 2284.38     318 2287.26
#Mann= 5 ,-1,0
       0     .06       0      50      .1       0  126.66    .045       0
  143.99      .1       0  145.48     .06       0
#XS Ineff= 2 , 0
          120.66  2258.2  149.99          2258.5
Permanent Ineff=
       F       F
Bank Sta=126.66,143.99
XS Rating Curve= 0 ,0
Exp/Cntr(USF)=0,0
Exp/Cntr=0.3,0.1

Type RM Length L Ch R = 1 ,207     ,135.2,133.9,130.4
BEGIN DESCRIPTION:
structure xs 1
END DESCRIPTION:
XS GIS Cut Line= 4
2208418.19595574561621.760908665 2208180.2908276561412.722341693
 2208089.6702962561465.6526311892208018.62256582561587.751435166
#Sta/Elev= 30
       0 2278.74    37.2 2265.46    43.3 2262.28      50    2257    52.9 2256.48
    82.6 2256.11   103.9 2259.32   122.1 2257.94   146.4 2258.27   174.7  2253.4
   194.4 2252.17   226.3 2247.49   248.4 2246.23   263.6 2247.02   276.8 2243.52
   296.6 2243.04   311.5 2246.49   325.5 2245.89   333.5 2244.15  345.892235.685
   352.2  2234.6   363.9 2235.68   369.8 2235.46   381.7 2239.32   418.7 2269.21
   428.2  2273.9   458.1 2277.02   495.1 2275.24     509 2282.01   562.9 2286.81
#Mann= 6 ,-1,0
       0     .06       0     140      .1       0  345.89    .045       0
   363.9      .1       0   396.7     .06       0  561.64      .1       0
Bank Sta=345.89,363.9
XS Rating Curve= 0 ,0
Exp/Cntr(USF)=0,0
Exp/Cntr=0.3,0.1

Type RM Length L Ch R = 1 ,73      ,,,
XS GIS Cut Line= 5
2208569.10687512561574.7836226312208450.65824227561396.011820546
2208125.94663162561277.5167552912208008.55446883561385.566664859
2207944.81886355561568.833649575
#Sta/Elev= 30
       0 2291.66    16.2 2283.12    40.3 2275.24      74 2259.43    82.6 2253.95
   107.5 2253.18   124.8 2247.13   160.3 2242.04   184.3 2231.86   189.4 2231.15
   255.4 2233.01   310.8  2230.8   351.1 2230.92   374.4 2232.73   391.7 2231.44
   402.7 2232.66   491.1  2233.2   560.1 2231.51   626.2 2232.11   637.6 2228.85
   654.5  2228.9   671.2 2228.06  677.762228.909   695.5 2240.04   709.3 2253.01
   723.5 2268.44   778.5 2271.85   820.9 2276.48   846.3 2276.65   913.7 2293.53
#Mann= 6 ,-1,0
       0     .06       0      60      .1       0   654.5    .045       0
  677.76      .1       0  769.66     .06       0  879.66      .1       0
Bank Sta=654.5,677.76
XS Rating Curve= 0 ,0
Exp/Cntr(USF)=0,0
Exp/Cntr=0.3,0.1
LCMann Table=0

Chan Stop Cuts=-1
Use User Specified Reach Order=0
Composite Channel Slope=5